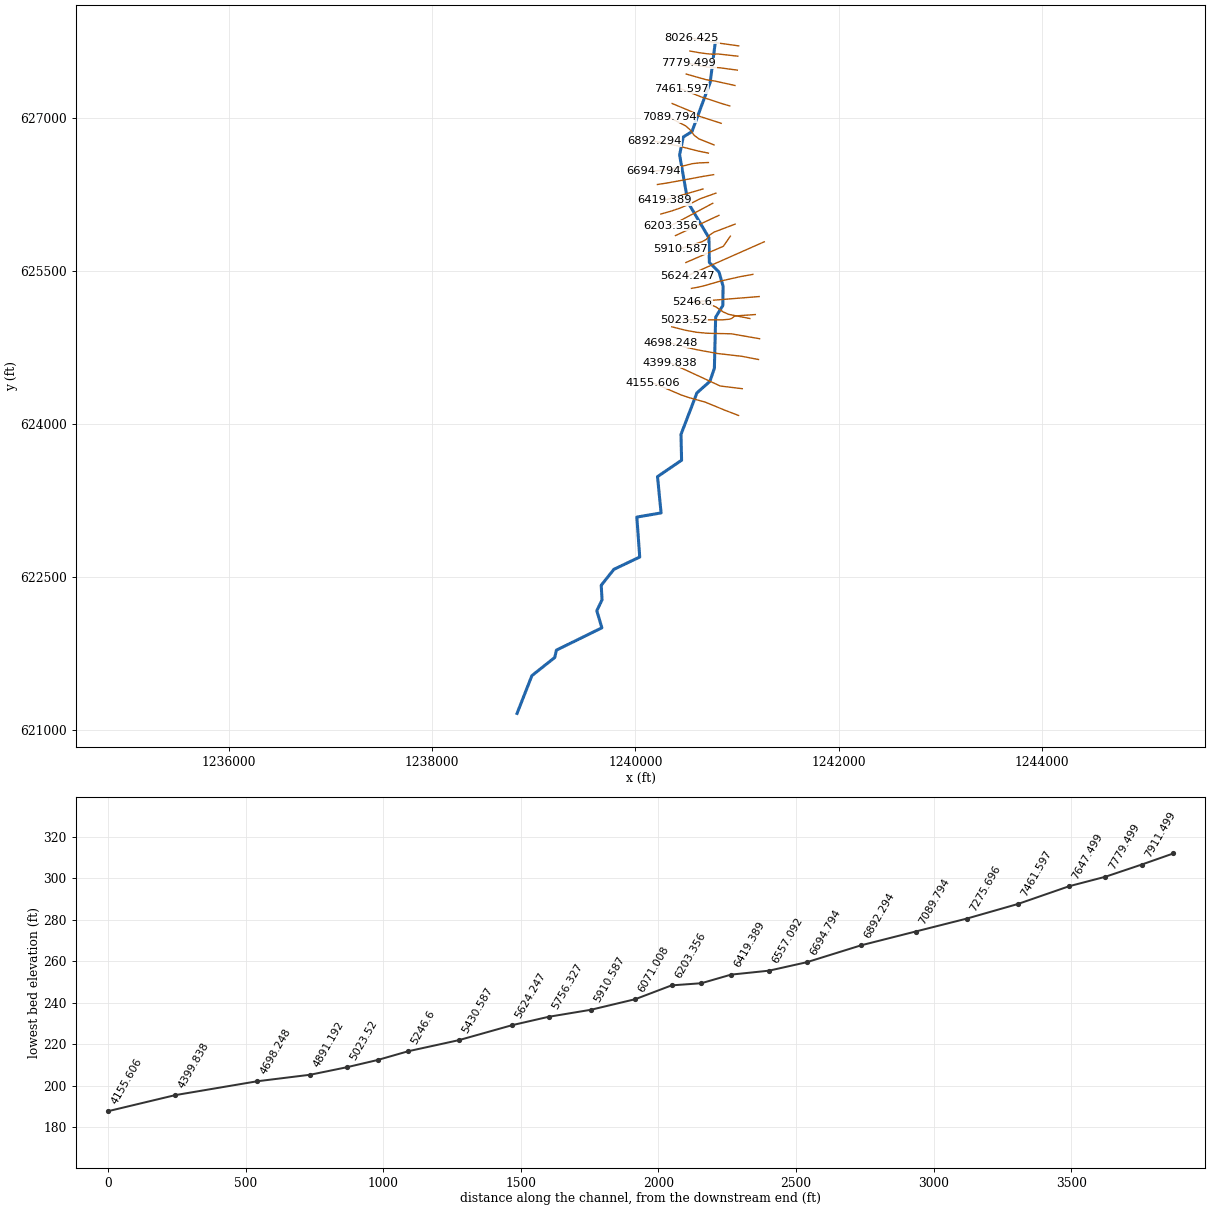
--- 336_ras.prj (project) ---

Proj Title=336
Current Plan=p01
Default Exp/Contr=0.3,0.1
English Units
Geom File=g01
Flow File=f01
Plan File=p01
Y Axis Title=Elevation
X Axis Title(PF)=Main Channel Distance
X Axis Title(XS)=Station
BEGIN DESCRIPTION:
RFD model 336 exported to HEC-RAS
END DESCRIPTION:

--- 336_ras.p01 (plan) ---

Plan Title=Plan 01
Program Version=4.10
Short Identifier=Plan 01
Geom File=g01
Flow File=f01
Subcritical Flow
Calc Critical at every XS
Secant Critical Depth

--- 336_ras.f01 (steady flow) ---

Flow Title=Flow 01
Program Version=5.01
Number of Profiles= 5
Profile Names=10yr,25yr,50yr,100yr,500yr
River Rch & RM=336,25,8026.425
  419.78  507.36  606.66   655.7  782.05
River Rch & RM=336,25,7911.499
  426.64  516.86  618.35  669.94   801.5
River Rch & RM=336,25,7779.499
  433.32  526.16   629.8  683.91  820.63
River Rch & RM=336,25,7647.499
  441.29  537.25  643.47  700.64  843.62
River Rch & RM=336,25,7461.597
  453.86  554.84  665.15  727.27  880.36
River Rch & RM=336,25,7275.696
  465.27  570.85  684.91  751.63  914.13
River Rch & RM=336,25,7089.794
  467.89  574.54  689.46  757.25  921.96
River Rch & RM=336,25,6892.294
  480.68  592.57  711.74  784.84  960.45
River Rch & RM=336,25,6694.794
  489.32   604.8  726.86  803.64  986.78
River Rch & RM=336,25,6557.092
  495.36  613.36  737.45  816.82 1005.31
River Rch & RM=336,25,6419.389
  500.11  620.11   745.8  827.23 1019.97
River Rch & RM=336,25,6311.373
  511.12  635.78   765.2   851.5 1054.23
River Rch & RM=336,25,6203.356
  518.45  646.24  778.16  867.74 1077.25
River Rch & RM=336,25,6071.008
  525.08  655.72   789.9  882.49 1098.21
River Rch & RM=336,25,5910.587
  528.89  661.17  796.66     891 1110.31
River Rch & RM=336,25,5756.327
  536.38  671.92  809.99  907.79 1134.26
River Rch & RM=336,25,5624.247
  539.02  675.71  814.69  913.72 1142.73
River Rch & RM=336,25,5430.587
  542.16  680.22  820.28  920.78 1152.84
Boundary for River Rch & Prof#=336,25,1
Up Type= 0
Dn Type= 2
Boundary for River Rch & Prof#=336,25,2
Up Type= 0
Dn Type= 2
Boundary for River Rch & Prof#=336,25,2
Up Type= 0
Dn Type= 2
Boundary for River Rch & Prof#=336,25,2
Up Type= 0
Dn Type= 2
Boundary for River Rch & Prof#=336,25,2
Up Type= 0
Dn Type= 2

--- 336_ras.g01 (geometry) ---

Geom Title=336
Program Version=4.10

River Reach=336,25
Reach XY= 30
1240786.34692075627744.312329909 1240736.3469241627352.645780951
1240557.18029624 626870.145929411240471.34698667626816.812614394
1240435.51365882626641.8126674031240518.01362088626175.146136869
1240723.84688338625828.4795670981240728.01354176625585.979638959
  1240823.013511625492.646330588 1240863.0134952625355.146370255
1240860.82661152625164.9604391371240789.99329573625049.960475311
1240777.49328481624548.2939579491240733.32662746624420.793997075
1240605.82666177624307.460701125 1240449.1600295 623900.79415974
1240454.99335372623647.460901415 1240218.3267522623486.627622759
1240253.32673151623130.7943940331240014.99346732623089.961079755
1240043.32678088622698.294528548 1239789.1601857 622577.46123848
1239664.54039183622420.9330869731239672.87371856622278.433129025
1239621.20706403622171.766495555 1239671.2070444622004.266543807
1239223.70717006621785.0999552341239207.87383933 621713.43331031
1238982.87390052 621535.100036481238837.04059943621165.286921744

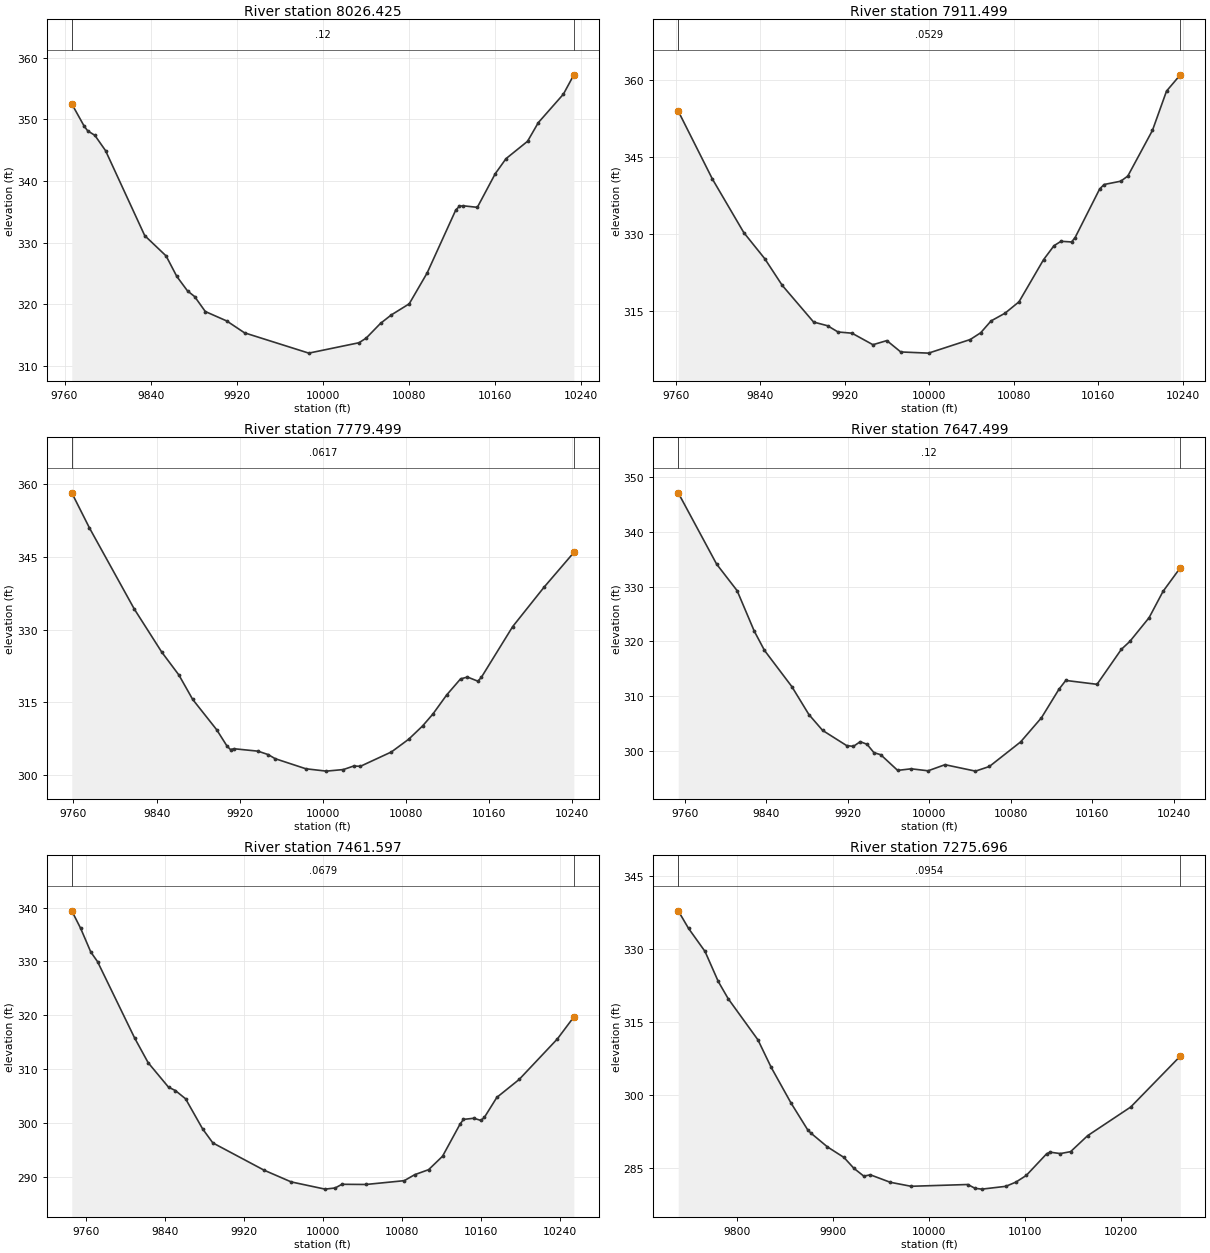
Type RM Length L Ch R = 1 ,8026.425,114.926100,114.926100,114.926100
XS GIS Cut Line= 5
1241017.05051285627710.1890321291240820.12127527627737.329990521
1240787.13766645627743.1398448371240785.17443568627743.521584213
1240556.46118152627784.106015133
#Sta/Elev= 30
9766.718352.48849778.223348.88029781.534348.11019788.158347.38729798.094344.9114
9834.524 331.1289854.395327.83449864.331324.51449874.266322.1691 9880.89321.2515
9890.825318.82419910.696317.29879927.256315.37189986.995312.081210033.65313.7654
10040.31314.516310053.64316.906110063.64318.2716 10080.3320.072310096.96325.0777
10123.61335.298110126.95335.879710130.28335.967410143.61335.714710160.27341.1683
10170.26343.607910190.26346.418410200.25349.441110223.58354.061610233.29357.1944
#Mann= 3 , 0 , 0
9766.718    0.12       09766.718    0.12       010233.29    0.12       0
#XS Ineff= 2 , 0
       0                               0
Bank Sta=9766.718,10233.29
Exp/Cntr=0.3,0.1

Type RM Length L Ch R = 1 ,7911.499,132.000000,132.000000,132.000000
XS GIS Cut Line= 6
1241008.26323529627609.1803480171240817.51022089627630.394462507
1240750.24964622627629.5708891981240705.92380413627632.890642334
 1240631.9594365627642.7960249011240536.77737716627659.429780497
#Sta/Elev= 30
9762.507353.88469794.843340.63899824.552330.19959844.359325.12049860.864319.9321
9890.573312.77359903.778312.05329913.681310.83859926.885310.60399946.691308.3575
9959.867309.15929973.002306.94739999.289306.717610038.73309.3674 10048.6310.6794
10058.47312.996410071.67 314.49910084.91 316.72610108.08324.924210118.01327.6556
10124.63328.510910134.56 328.38110137.87329.201510161.16338.701210165.37339.5773
10181.15340.224210187.81341.221410211.12350.124310224.45357.786410237.48360.9505
#Mann= 3 , 0 , 0
9762.507  0.0529       09762.507  0.0529       010237.48  0.0529       0
#XS Ineff= 2 , 0
       0                               0
Bank Sta=9762.507,10237.48
Exp/Cntr=0.3,0.1

Type RM Length L Ch R = 1 ,7779.499,132.000000,132.000000,132.000000
XS GIS Cut Line= 6
1241002.86701885627472.3165206291240828.51241235 627495.93135805
1240739.09515234627499.8315043281240708.20237551627503.029253765
1240623.74087931627517.2278259181240524.86398937627538.097797685
#Sta/Elev= 30
9758.364358.16339775.417350.91839818.457334.24869844.943 325.3559861.497320.6209
 9874.74315.60049897.916309.33159907.848305.96299911.159305.2574 9914.47305.4351
9937.626 304.9339947.501304.22149954.085303.3903 9983.68301.306210003.37300.8205
10019.78301.144410029.65301.866110036.25301.821210066.03304.773310082.66307.3932
10095.97310.114210105.95312.581710119.26 316.52610132.57319.821410139.22320.2083
10149.27319.354510152.62320.1484 10182.8330.6138   10213338.730810241.63345.8748
#Mann= 3 , 0 , 0
9758.364  0.0617       09758.364  0.0617       010241.63  0.0617       0
#XS Ineff= 2 , 0
       0                               0
Bank Sta=9758.364,10241.63
Exp/Cntr=0.3,0.1

Type RM Length L Ch R = 1 ,7647.499,185.901400,185.901400,185.901400
XS GIS Cut Line= 6
1240980.13535587627321.8751891321240783.77645633627364.863409889
1240739.72355012627371.5965268121240737.73899438 627371.84459634
  1240693.810989627379.2579683781240500.45747344627434.175092516
#Sta/Elev= 30
9753.426347.13719791.116334.10419811.267329.2421 9828.06321.85939838.135318.3201
9865.003311.70129881.796306.5798 9895.23303.6924 9918.74300.92539925.457300.7644
9932.174301.63039938.891301.14869945.608 299.6279952.325299.24139968.945296.3765
9982.221296.66879998.815296.304210015.44297.418910045.38 296.24310059.02297.0924
10089.72301.588610110.18306.006710127.23311.181910134.05312.828210164.75312.1183
10188.62318.5125   10197319.966510215.91324.310610229.55329.105710246.55333.4352
#Mann= 3 , 0 , 0
9753.426    0.12       09753.426    0.12       010246.55    0.12       0
#XS Ineff= 2 , 0
       0                               0
Bank Sta=9753.426,10246.55
Exp/Cntr=0.3,0.1

Type RM Length L Ch R = 1 ,7461.597,185.901500,185.901500,185.901500
XS GIS Cut Line= 6
1240928.99245616627121.3908126621240845.85973541627145.865277859
1240725.45580086627185.7068564541240687.18290289627197.035285519
1240656.20062881627206.6363259281240448.84323264627288.541047295
#Sta/Elev= 30
9745.601339.41919754.608336.15869764.868331.76459771.708329.97329809.329315.7675
9823.009311.18229843.647306.63079850.559306.00929860.926304.47649878.205298.8755
9888.572296.26829940.409291.20629967.966289.019610002.24287.677910012.53287.8928
10019.39288.577110043.74288.542510082.54289.251110093.12290.363710107.23291.2974
10121.34293.792610138.98299.733210142.51300.640410153.09300.855810160.15300.4528
10163.67300.999610176.36 304.73410198.95308.064910237.75315.612310254.39 319.693
#Mann= 3 , 0 , 0
9745.601  0.0679       09745.601  0.0679       010254.39  0.0679       0
#XS Ineff= 2 , 0
       0                               0
Bank Sta=9745.601,10254.39
Exp/Cntr=0.3,0.1

Type RM Length L Ch R = 1 ,7275.696,185.901400,185.901400,185.901400
XS GIS Cut Line= 6
1240845.23389694626950.9043539951240629.00724686627020.021763728
1240610.77223989627029.4858112951240584.11800605627050.235487368
1240561.73150391627062.1594076491240362.09269447627145.204273251
#Sta/Elev= 30
9738.548 337.8639749.239334.26359766.461329.50629780.238323.32999790.572319.7882
9821.571311.32079835.348305.67319856.015298.33239873.236292.86329876.681292.1525
9893.903 289.3139911.125287.14259921.458284.91389931.791283.2962 9938.68 283.561
9959.346282.0309 9981.07281.205510040.11281.571710047.71280.787810054.81280.6207
10079.69281.195610090.22282.062410101.01283.429910122.33287.905310125.88288.2171
10136.54287.9341 10147.2288.327810164.97291.620910209.81297.507610261.47307.9764
#Mann= 3 , 0 , 0
9738.548  0.0954       09738.548  0.0954       010261.47  0.0954       0
#XS Ineff= 2 , 0
       0                               0
Bank Sta=9738.548,10261.47
Exp/Cntr=0.3,0.1

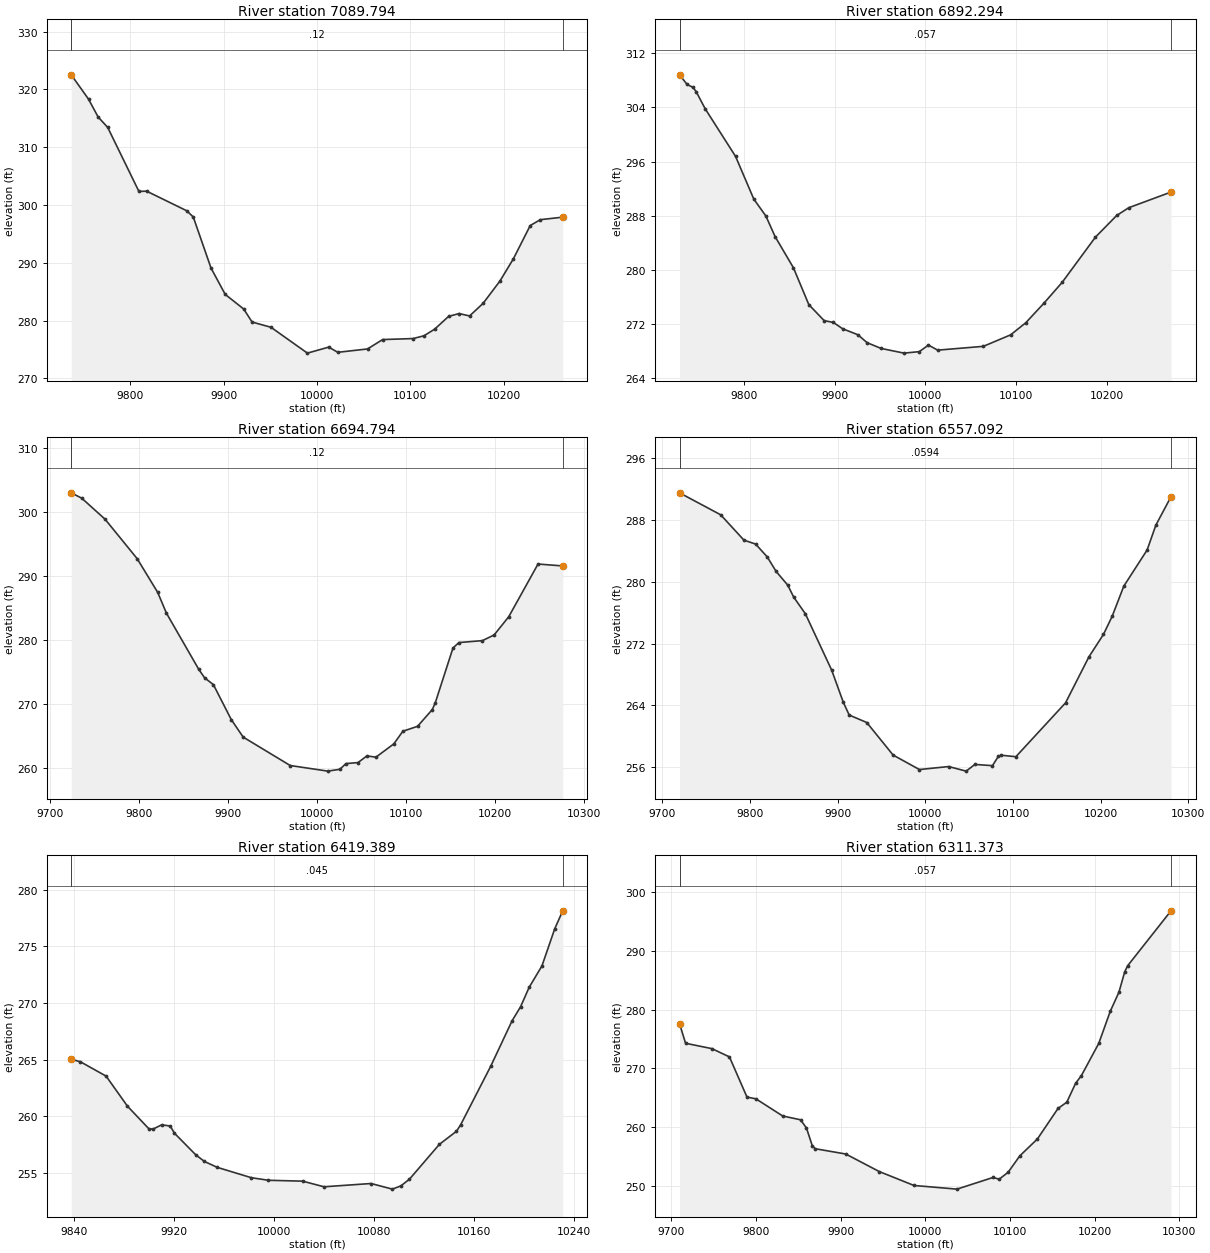
Type RM Length L Ch R = 1 ,7089.794,197.500000,197.500000,197.500000
XS GIS Cut Line= 6
1240774.04648567626739.1816496531240625.57706694626798.271171321
1240578.74017666626833.3936686691240542.71056032626883.648643222
 1240496.1759053626925.0940988111240334.25114243627008.587151358
#Sta/Elev= 30
9736.993322.52319755.488318.31919765.751315.23549776.015313.42779809.432302.3523
9817.714 302.3999860.635299.00659867.618297.9334 9886.63289.09259901.812284.5406
9921.586282.01329930.565279.76089950.795278.85589989.776274.383510012.62275.4226
 10022.3274.523810054.13275.106410070.29276.730810102.86276.902210114.57277.3826
10126.01278.534410140.95 280.74310152.16281.226310163.36280.813910177.79282.9844
10195.82286.842610210.25 290.69610228.28296.4508 10239.1297.468210263.06297.9008
#Mann= 3 , 0 , 0
9736.993    0.12       09736.993    0.12       010263.06    0.12       0
#XS Ineff= 2 , 0
       0                               0
Bank Sta=9736.993,10263.06
Exp/Cntr=0.3,0.1

Type RM Length L Ch R = 1 ,6892.294,197.500000,197.500000,197.500000
XS GIS Cut Line= 6
1240718.53995742626658.7903471691240619.67069847626678.684095474
1240455.62647705626720.4786555811240453.69232799626720.987642237
 1240418.1117376 626729.690395391240188.98195469626774.747598163
#Sta/Elev= 30
9728.865308.79479737.189307.38559743.883306.92859747.229306.31279757.269303.7673
9790.735296.75399810.814290.46849824.201287.95759834.293284.94129854.607280.3181
9871.535274.89739888.464272.53569898.621272.26989908.777271.34349925.706 270.449
9935.863269.27929951.279268.4355 9976.49267.74179993.418267.960410003.57268.9265
10013.71268.1815 10064.1268.742510094.19270.437310110.91272.219110130.97275.1101
10151.04278.176110187.82284.857410211.22288.0453 10224.6289.194710271.15291.5006
#Mann= 3 , 0 , 0
9728.865   0.057       09728.865   0.057       010271.15   0.057       0
#XS Ineff= 2 , 0
       0                               0
Bank Sta=9728.865,10271.15
Exp/Cntr=0.3,0.1

Type RM Length L Ch R = 1 ,6694.794,137.702600,137.702600,137.702600
XS GIS Cut Line= 6
1240718.91570175626566.4364138371240629.63163411626562.972047515
1240559.51521447626554.9914441151240354.44008948626503.583589509
1240269.32615284626490.770454189 1240174.1787894626482.215029293
#Sta/Elev= 30
 9723.48303.06019735.307 302.2229761.574298.9331 9797.69 292.7679820.718287.5171
9830.624284.25379866.946275.4881 9873.55274.15479883.457273.08959903.554267.6288
9916.952264.89389969.884260.453410012.18259.575710025.79259.8629 10032.6260.7513
10046.16260.911510056.26261.955510066.36261.755110086.55263.842110096.62265.8036
10113.21266.5787 10129.8269.202410133.12270.248610153.03278.805410159.66279.6622
10186.17279.966410199.34280.849410215.81283.702310248.76291.934410276.54291.6362
#Mann= 3 , 0 , 0
 9723.48    0.12       0 9723.48    0.12       010276.54    0.12       0
#XS Ineff= 2 , 0
       0                               0
Bank Sta=9723.48,10276.54
Exp/Cntr=0.3,0.1

Type RM Length L Ch R = 1 ,6557.092,137.702600,137.702600,137.702600
XS GIS Cut Line= 6
1240769.85370585626447.4730249011240677.90223032 626432.56351225
1240494.82074567626398.6156602951240492.83557289626398.372577972
1240321.04555421 626367.034374181240217.58118748626350.783183254
#Sta/Elev= 30
9719.645291.53859766.602 288.6919793.192285.40199806.487   284.99819.809283.2203
9829.819281.36029843.166279.5716 9849.84 278.0399863.187275.87569893.218268.5681
9906.565264.38359913.238262.74429933.259 261.7799963.289257.5633 9993.32255.6841
10026.66256.072710046.66255.478410056.67256.347410076.68256.186510083.35257.3861
10086.68257.540410103.36257.344210160.05264.325210186.69270.280210203.29273.1896
10213.26 275.54610226.54279.452810253.11284.127610263.07287.344410280.36291.0375
#Mann= 3 , 0 , 0
9719.645  0.0594       09719.645  0.0594       010280.36  0.0594       0
#XS Ineff= 2 , 0
       0                               0
Bank Sta=9719.645,10280.36
Exp/Cntr=0.3,0.1

Type RM Length L Ch R = 1 ,6419.389,108.016500,108.016500,108.016500
XS GIS Cut Line= 2
1240664.96544367626307.2575737681240287.61167765 626197.08129172
#Sta/Elev= 30
 9837.66265.04759845.036264.81839865.543263.55439882.632260.89899899.721258.9073
9903.139258.87979909.975259.2513 9916.81 259.1489920.228258.51029937.317256.5977
9944.153256.02149954.406255.49819981.749254.5829 9995.42254.355610022.76254.2792
10039.85253.781110077.45254.071310094.54253.574910101.37253.864710108.21 254.457
10132.13257.5317 10145.8258.683710149.22 259.27510173.15264.419710190.24268.4339
10197.07269.679610203.91271.392310214.16273.286910224.41276.571510230.77 278.149
#Mann= 3 , 0 , 0
 9837.66   0.045       0 9837.66   0.045       010230.77   0.045       0
#XS Ineff= 2 , 0
       0                               0
Bank Sta=9837.66,10230.77
Exp/Cntr=0.3,0.1

Type RM Length L Ch R = 1 ,6311.373,108.016400,108.016400,108.016400
XS GIS Cut Line= 6
1240792.64042814626266.3893611341240635.94020857626210.559319735
1240534.22677335626159.1288256671240438.02597342626118.950507752
1240354.10093646626090.3736739961240250.97489231626061.250544055
#Sta/Elev= 30
9709.741277.60879716.901 274.2699747.983 273.3569768.704271.94879789.425265.1027
9799.951264.80549831.565261.88399852.641 261.2349859.666 259.8419866.692256.7504
9870.204256.30079906.128255.4007 9945.63252.41659986.701250.042310037.46249.4201
10080.16251.411510087.28251.110410097.86252.284810111.72255.089810132.52257.9738
10156.78263.160210167.18264.229910177.57267.441710184.48268.776710204.94274.2474
10218.57279.7342 10228.8282.981310235.62286.453710239.03287.470610290.26296.8332
#Mann= 3 , 0 , 0
9709.741   0.057       09709.741   0.057       010290.26   0.057       0
#XS Ineff= 2 , 0
       0                               0
Bank Sta=9709.741,10290.26
Exp/Cntr=0.3,0.1

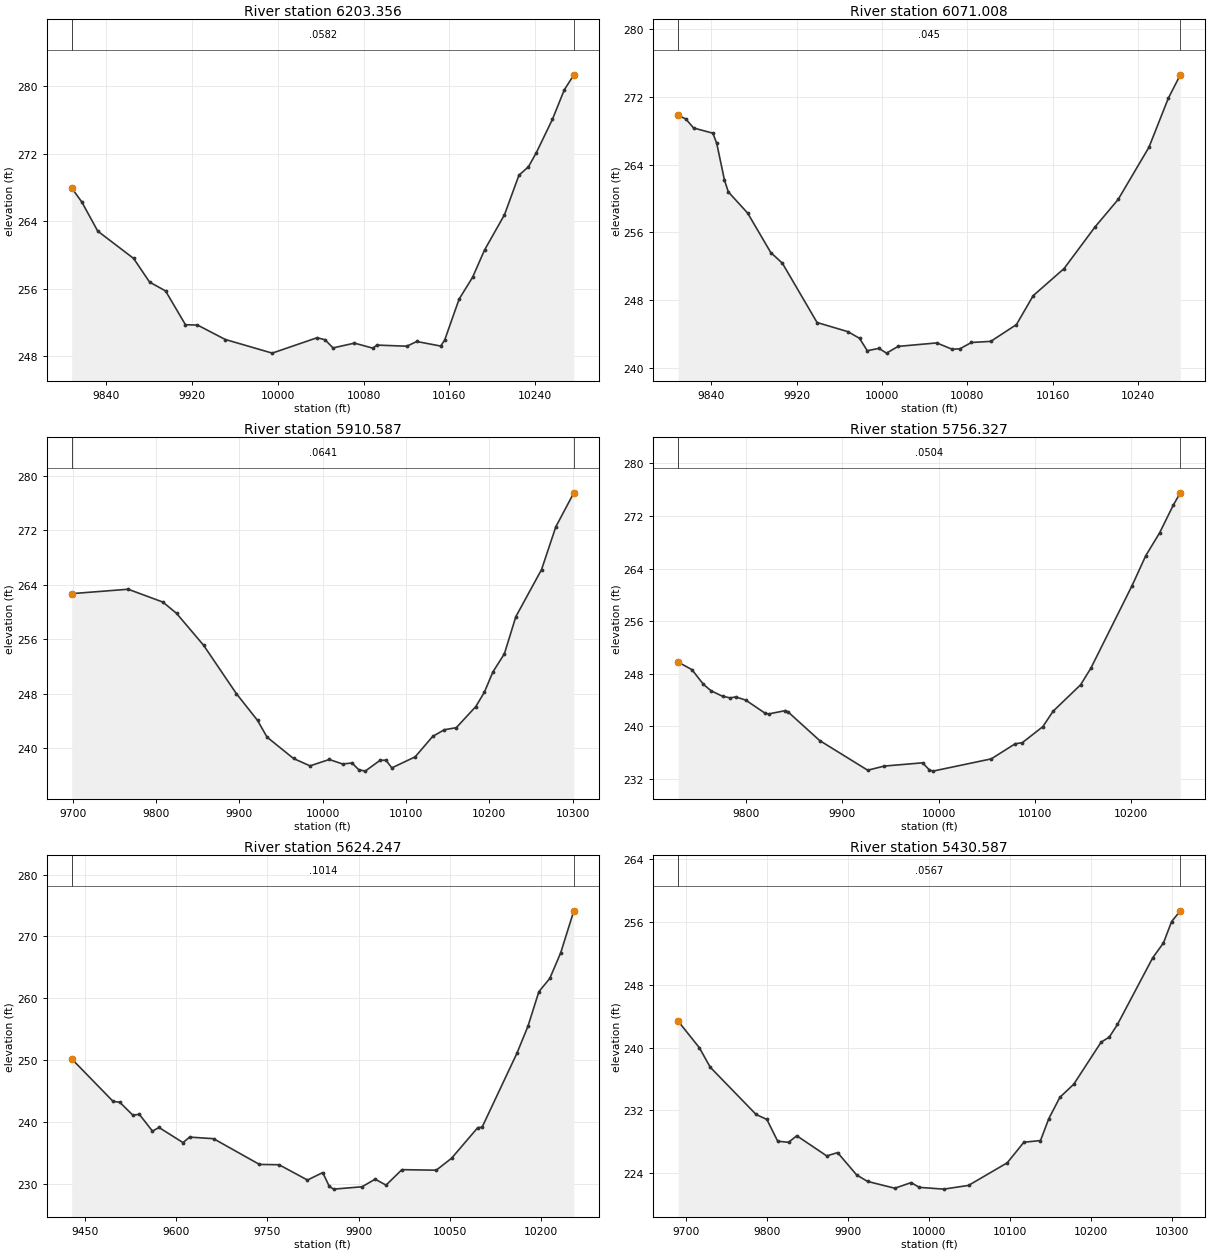
Type RM Length L Ch R = 1 ,6203.356,132.348100,132.348100,132.348100
XS GIS Cut Line= 2
1240761.36969045626166.7828141451240348.20863274625946.430250034
#Sta/Elev= 30
9807.798267.9422 9817.25266.28639832.123262.83399865.588259.59689880.461256.7975
9895.334 255.7549913.926 251.745 9925.08251.71419951.108249.99799994.811248.3846
10036.64250.207810044.07 249.968 10051.5249.0012 10071.5 249.56910088.68248.9703
10092.42249.3367 10120.3249.204510129.59249.7622 10151.9249.221610155.61249.9295
 10169.1254.790110181.64257.3621 10192.8260.599610211.39264.771910224.88269.4569
 10233.7270.446810241.13272.132610256.01276.052710267.16279.562410276.05 281.339
#Mann= 3 , 0 , 0
9807.798  0.0582       09807.798  0.0582       010276.05  0.0582       0
#XS Ineff= 2 , 0
       0                               0
Bank Sta=9807.798,10276.05
Exp/Cntr=0.3,0.1

Type RM Length L Ch R = 1 ,6071.008,160.421400,160.421400,160.421400
XS GIS Cut Line= 2
 1240821.9666456626048.3433109521240395.03355265625850.026003256
#Sta/Elev= 30
9808.924269.84219816.203269.39379823.438268.33479841.526 267.7179845.143266.5061
9852.378262.16739855.996260.77059874.083258.27349895.788 253.5999906.641252.3456
9939.164245.32659968.139244.24099978.991243.45749986.226241.99049997.079 242.266
10004.31241.704810015.17242.502710051.34242.911910065.81242.162910073.05242.2192
 10083.9 242.96410101.99243.095610126.07245.082410141.78248.503910170.72251.7084
10199.66256.617510221.37 259.87710250.31266.061410268.39271.840710279.67274.6215
#Mann= 3 , 0 , 0
9808.924   0.045       09808.924   0.045       010279.67   0.045       0
#XS Ineff= 2 , 0
       0                               0
Bank Sta=9808.924,10279.67
Exp/Cntr=0.3,0.1

Type RM Length L Ch R = 1 ,5910.587,154.259700,154.259700,154.259700
XS GIS Cut Line= 6
1240981.23438239625962.2862672651240772.95104957 625883.57059085
1240731.37864882625855.7207844681240700.20644248625814.211868412
1240659.25097823625791.0578141191240440.38270696 625719.19854211
#Sta/Elev= 30
9698.574262.67549766.435263.32399808.074261.43939824.463259.78669857.086255.0782
9896.277248.00169921.699244.06999933.127241.61369964.885238.47639984.693237.3923
10007.84238.326810023.83237.667610035.21237.816310043.06236.837510050.95236.6195
10068.83238.210210075.92238.220210082.92237.095510110.91 238.714 10131.9 241.707
 10145.9242.694310160.29242.997910183.74 246.10410193.89248.175910204.33251.2019
10218.05253.850610231.78259.294810262.66266.216810279.81272.500210301.41277.4779
#Mann= 3 , 0 , 0
9698.574  0.0641       09698.574  0.0641       010301.41  0.0641       0
#XS Ineff= 2 , 0
       0                               0
Bank Sta=9698.574,10301.41
Exp/Cntr=0.3,0.1

Type RM Length L Ch R = 1 ,5756.327,132.080000,132.080000,132.080000
XS GIS Cut Line= 3
1240934.89733467625844.5171891451240866.03715837625745.358535305
1240496.94661355625585.602926329
#Sta/Elev= 30
9728.878249.78849743.248 248.6429755.231246.4083 9763.22245.42239775.203244.5909
9783.138244.3457 9788.89244.49689799.169244.01659819.141242.04929823.135241.9044
9840.657242.41699843.107242.24929876.217237.86649926.267233.35039943.544233.9816
9983.466234.47559990.616233.37289994.191233.212210054.97 235.07610079.99237.3832
10087.14237.520910108.59 239.96610119.32242.317610147.92246.331110158.64 248.861
10201.54261.410810215.84 265.97110230.14269.411210244.44273.643810251.78 275.521
#Mann= 3 , 0 , 0
9728.878  0.0504       09728.878  0.0504       010251.78  0.0504       0
#XS Ineff= 2 , 0
       0                               0
Bank Sta=9728.878,10251.78
Exp/Cntr=0.3,0.1

Type RM Length L Ch R = 1 ,5624.247,193.660300,193.660300,193.660300
XS GIS Cut Line= 2
1241268.18058789625789.4290481211240513.47305584625456.145794913
#Sta/Elev= 30
 9428.38250.2295 9496.59243.34519507.349243.22739528.868241.13729539.628241.2622
9561.147238.55549571.906239.14349611.358236.69779622.117237.58859661.569237.3298
9736.885233.17529769.164233.12329815.788230.65169840.894231.85819851.654229.6188
9858.827229.18439905.451229.5637 9926.97230.79359944.903229.8312 9970.95232.3302
10027.39232.2408 10052.5234.171210095.54239.117910102.71239.191810160.09251.1772
10178.03255.502410195.96261.081910213.89263.219810231.82267.3649 10253.4274.1382
#Mann= 3 , 0 , 0
 9428.38  0.1014       0 9428.38  0.1014       0 10253.4  0.1014       0
#XS Ineff= 2 , 0
       0                               0
Bank Sta=9428.38,10253.4
Exp/Cntr=0.3,0.1

Type RM Length L Ch R = 1 ,5430.587,183.987100,183.987100,183.987100
XS GIS Cut Line= 6
1241156.15908207625469.6452482221241034.57242575 625447.83950033
1240834.88021862625403.3148288651240672.40462552625356.832364053
1240612.30214019625343.1869505471240552.15478385625332.482457348
#Sta/Elev= 30
9690.064243.3665 9716.31239.97319729.643237.50089786.307231.4667 9799.64230.8291
9812.973228.05879826.414227.9166  9836.5228.75389873.479226.18539886.926226.6021
9910.459223.75649923.906222.92999957.523222.06149977.694222.78019987.779222.1735
10018.01221.947610048.49222.422210096.31225.302310116.83227.924910137.35228.1426
10147.61230.936510161.29233.657210178.39235.321110212.18240.689210222.27241.3302
10232.37242.944510275.84251.438910289.17253.344810299.17256.062710309.92257.4296
#Mann= 3 , 0 , 0
9690.064  0.0567       09690.064  0.0567       010309.92  0.0567       0
#XS Ineff= 2 , 0
       0                               0
Bank Sta=9690.064,10309.92
Exp/Cntr=0.3,0.1

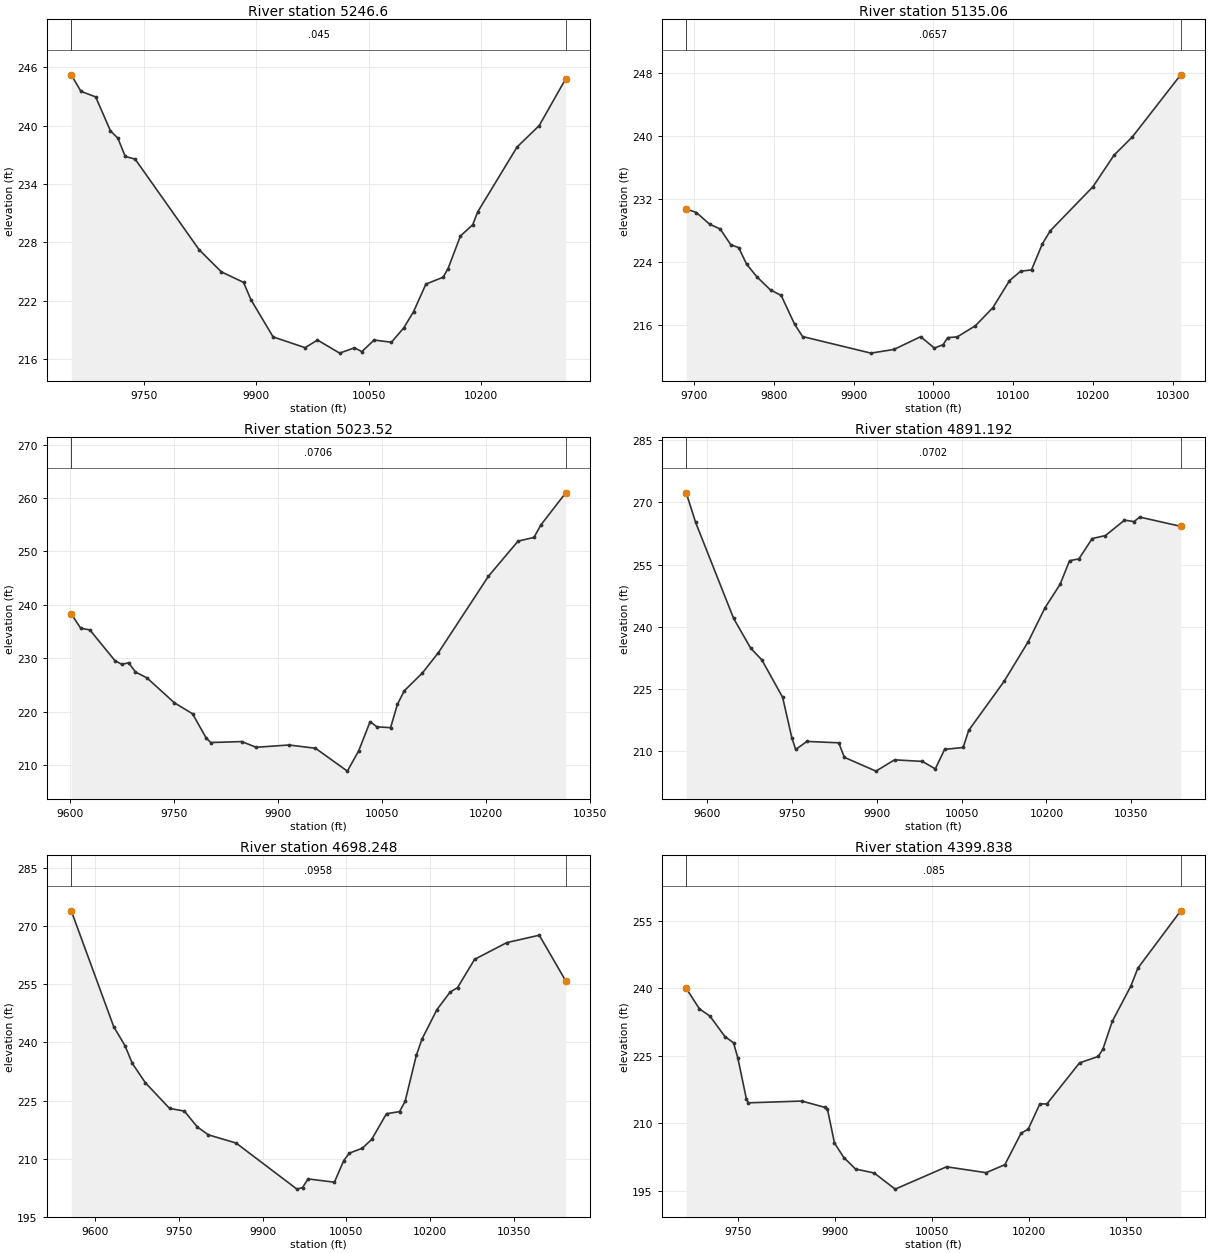
Type RM Length L Ch R = 1 ,  5246.6,111.540000,111.540000,111.540000
XS GIS Cut Line= 2
1241218.60126094625252.3196731131240560.29797573625199.985939152
#Sta/Elev= 30
9652.715245.23539665.572243.54219685.319242.96139705.067239.4704 9714.94238.7203
9724.814236.83519737.978236.56649823.549 227.232 9853.17224.9605 9882.79223.8805
9892.664222.09729922.285218.2674 9965.07 217.1599981.526217.945710011.15216.5977
10030.89217.145110040.77216.752610057.22217.945310080.26 217.71610096.72219.1902
10109.88220.866910126.34223.700310149.38224.410210155.96225.303610172.41228.6459
10188.87229.807810195.45231.120910248.11237.807110277.66240.0123 10313.1 244.831
#Mann= 3 , 0 , 0
9652.715   0.045       09652.715   0.045       0 10313.1   0.045       0
#XS Ineff= 2 , 0
       0                               0
Bank Sta=9652.715,10313.1
Exp/Cntr=0.3,0.1

Type RM Length L Ch R = 1 , 5135.06,111.540100,111.540100,111.540100
XS GIS Cut Line= 6
1241126.56378561625036.7196790091240916.59375467625078.084192819
1240864.06100679625101.7839576821240791.46793098625151.097897838
1240729.62823822625175.4951615021240538.43990567625200.717882731
#Sta/Elev= 30
9690.125230.72199702.886230.26229719.443228.77599732.689228.16739745.935 226.162
 9755.87225.79069765.804223.68259779.124222.02749795.793220.39489809.129219.7055
9825.841216.06449835.943214.46639921.612212.35559950.549212.82779983.996214.4513
10001.08212.999910012.08213.431210017.95214.3317 10029.8214.4236 10052.6215.8452
10074.28218.120810095.31221.585810109.18222.785510122.89222.955610136.41226.2544
10146.55227.954810199.88233.544810226.31237.5625 10249.4239.904610309.88247.7978
#Mann= 3 , 0 , 0
9690.125  0.0657       09690.125  0.0657       010309.88  0.0657       0
#XS Ineff= 2 , 0
       09941.259                       0
Bank Sta=9690.125,10309.88
Exp/Cntr=0.3,0.1

Type RM Length L Ch R = 1 , 5023.52,132.328000,132.328000,132.328000
XS GIS Cut Line= 6
1241180.03956226625076.0376218411240979.09097388625061.853015617
1240947.67619434625037.6878005711240926.40899372625029.954273105
1240848.10702786625023.1874365511240477.66576421625026.458294928
#Sta/Elev= 30
9601.797238.30599615.456235.62589628.612 235.3179664.791229.55299674.658228.8682
9684.525229.15579694.392227.43079710.837226.34199750.305221.68389776.617219.6122
9796.351215.06059802.929214.22659847.517214.40549868.296 213.3389915.741213.7654
 9953.88213.15369999.817208.870710016.22212.684510032.63 218.13610042.47217.1714
10062.16 217.006   10072221.378810081.85223.9067 10108.1227.266910131.07231.0598
10203.25245.373310245.91 251.94510268.88252.635410278.72254.955810314.65260.9861
#Mann= 3 , 0 , 0
9601.797  0.0706       09601.797  0.0706       010314.65  0.0706       0
#XS Ineff= 2 , 0
       0 9949.23                       0
Bank Sta=9601.797,10314.65
Exp/Cntr=0.3,0.1

Type RM Length L Ch R = 1 ,4891.192,192.943700,192.943700,192.943700
XS GIS Cut Line= 6
1241222.09766299624838.8733846951240943.86822985624887.091520035
1240709.20040391624892.2357745071240603.35690867624901.942687916
1240493.54578194624921.7074791271240358.28860126624955.942723162
#Sta/Elev= 30
9562.605272.25489579.293265.11539646.383 242.0529676.417234.9056 9696.44232.0294
9733.102223.05269749.659213.19029756.281210.47629776.149212.4169 9832.44212.0829
9842.373208.5915 9898.27205.26619931.138207.98369980.356207.609110003.32205.8051
10019.73210.500310052.53210.959710062.38215.076910124.81226.842210167.72236.4332
10197.51244.6206 10224.1250.235610240.72255.904510257.41256.368910280.84261.2499
10304.31261.9666   10338265.681610354.85265.3342   10365266.417810437.42264.1895
#Mann= 3 , 0 , 0
9562.605  0.0702       09562.605  0.0702       010437.42  0.0702       0
#XS Ineff= 2 , 0
       09902.168                       0
Bank Sta=9562.605,10437.42
Exp/Cntr=0.3,0.1

Type RM Length L Ch R = 1 ,4698.248,298.409900,298.409900,298.409900
XS GIS Cut Line= 6
1241211.23544179624634.9774943811241047.48941829624666.415982696
1240808.04078951624693.8246739911240606.67866635624730.627956895
1240479.46675184 624759.329923661240343.31971685624798.198055977
#Sta/Elev= 30
9557.724 273.993 9633.67244.06799653.694239.20049667.019234.56269690.339229.5806
9733.589222.95859760.073222.26629783.247218.1584 9803.11216.1302 9852.65214.0052
9961.462202.1075 9971.44202.51269981.477204.745610028.45203.891510045.18209.4801
10055.16211.399310078.44212.679110095.07214.943210121.68221.594410144.97222.1173
10154.95224.784310174.94236.625310184.99240.820110211.78248.4575 10235.3252.9763
 10248.8254.162210279.16261.456110336.93265.788810394.93267.690410442.29255.8981
#Mann= 3 , 0 , 0
9557.724  0.0958       09557.724  0.0958       010442.29  0.0958       0
#XS Ineff= 2 , 0
       0                               0
Bank Sta=9557.724,10442.29
Exp/Cntr=0.3,0.1

Type RM Length L Ch R = 1 ,4399.838,244.232000,244.232000,244.232000
XS GIS Cut Line= 3
1241052.06396794 624348.87416029 1240835.9181346624374.915826976
1240338.52230129624604.082493618
#Sta/Elev= 30
9669.703240.02259690.012235.48219706.535 233.8289729.667229.29269742.885227.9227
9749.494224.60649762.712215.53089766.017 214.5819848.631214.97119884.981213.5455
9888.367213.12959899.204205.63439913.653202.42779931.715199.87089960.613198.9893
9993.124195.401410072.59200.3639   10134199.0564 10162.9200.832410187.99207.8286
10199.03 208.72510217.09214.344610227.92214.3285 10278.5 223.45910307.39224.8771
10314.62 226.49710329.12232.669210357.97240.5405 10368.8244.505410435.06257.2418
#Mann= 3 , 0 , 0
9669.703   0.085       09669.703   0.085       010435.06   0.085       0
#XS Ineff= 2 , 0
       0                               0
Bank Sta=9669.703,10435.06
Exp/Cntr=0.3,0.1

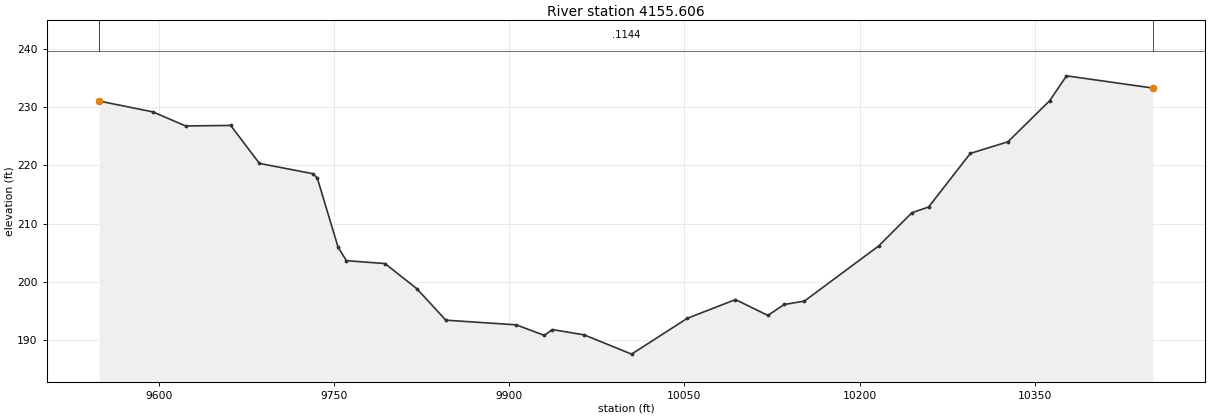
Type RM Length L Ch R = 1 ,4155.606,0.000000,0.000000,0.000000
XS GIS Cut Line= 6
1241015.65935879624086.469013129 1240883.3962643624136.791338489
1240686.57760356 624217.54060506  1240529.871334624260.630356681
 1240448.8754266624288.4075442061240173.54486233624405.340849089
#Sta/Elev= 30
9549.201231.04869595.009229.19599623.092226.78089661.705 226.8639686.277220.3579
9732.332218.57429735.878217.82059753.609205.98169760.702203.67089793.731203.1764
9820.988198.87149845.811193.4623 9906.02192.66489930.122190.85599937.009191.8496
 9964.21190.943510004.82187.638910052.37193.771710093.71196.995210121.45 194.274
10135.33196.152610152.69196.736810216.46206.221910244.72211.893410258.98212.8734
10294.69222.066310326.89224.061510362.68 231.12210376.99235.3746 10450.8233.2822
#Mann= 3 , 0 , 0
9549.201  0.1144       09549.201  0.1144       0 10450.8  0.1144       0
#XS Ineff= 2 , 0
       0                               0
Bank Sta=9549.201,10450.8
Exp/Cntr=0.3,0.1